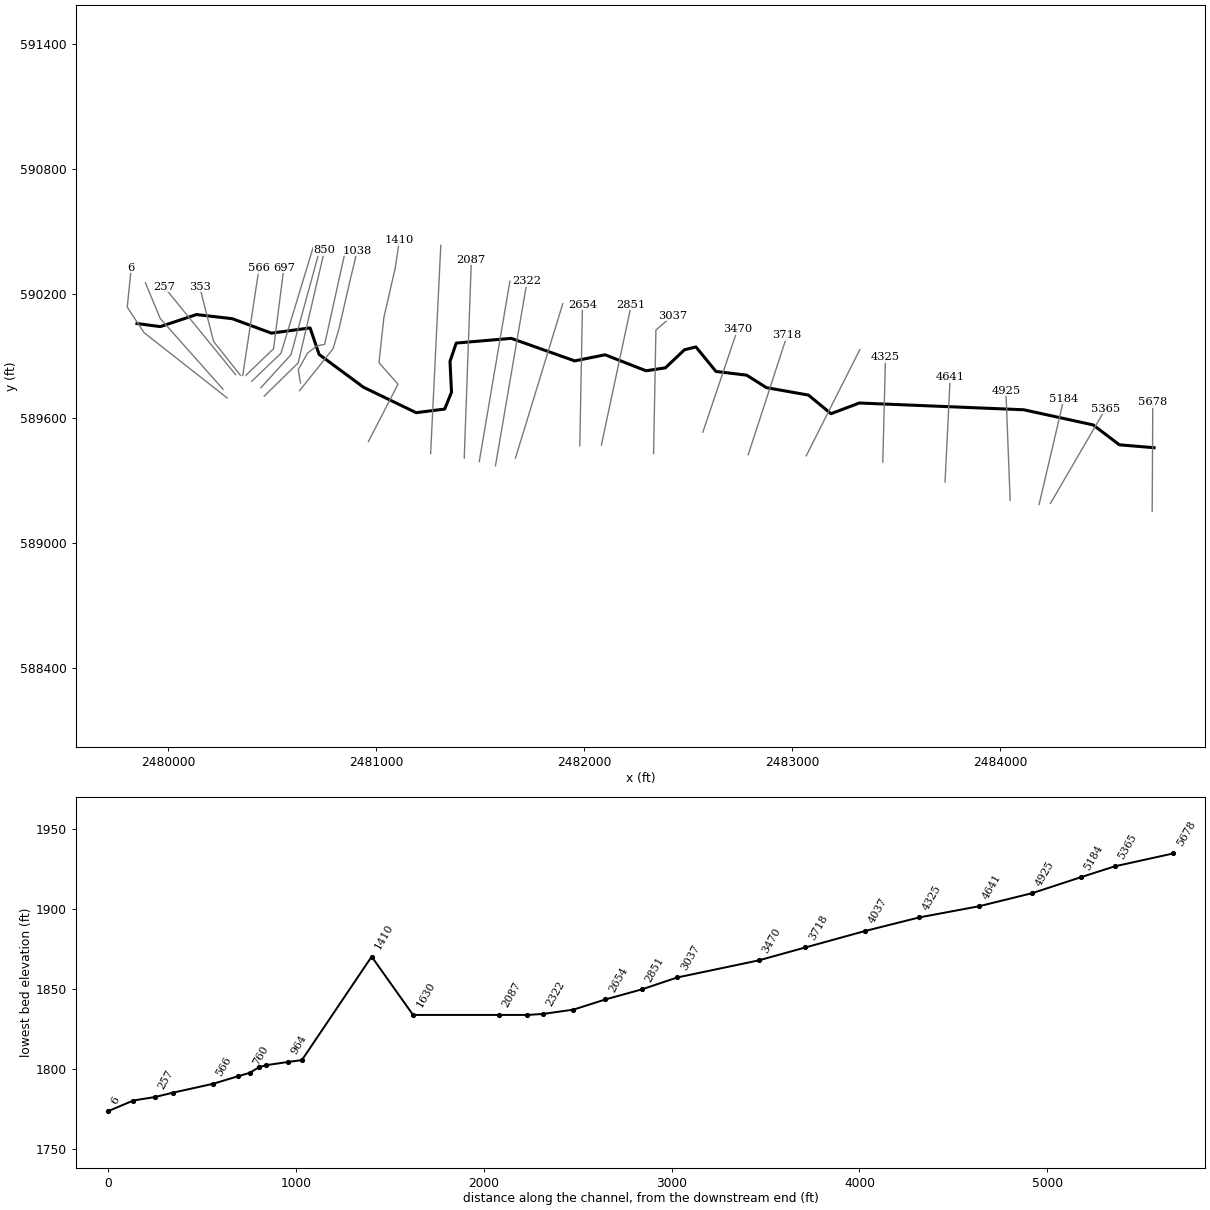
--- HAWESRN_T1.prj (project) ---

Proj Title=HAWESRN_T1
Current Plan=p01
Default Exp/Contr=0,0
English Units
Geom File=g01
Flow File=f01
Plan File=p01
BEGIN DESCRIPTION:
Stream Name: Hawes Run Tributary 1
Flood Zone: Approximate
Pendleton County, West Virginia
HEC-RAS Version: 5.0.7
Hydrology Method:
Regression equation
END DESCRIPTION:
DSS File=dss
DSS Export Rating Curves= 0
DSS Export Rating Curve Sorted= 0
DSS Export Volume Flow Curves= 0
DXF OffsetX= 0
DXF OffsetY= 0
DXF ScaleX= 0
DXF ScaleY= 0

--- HAWESRN_T1.p01 (plan) ---

Plan Title=Floodplain
Program Version=5.07
Short Identifier=Floodplain
Geom File=g01
Flow File=f01
Subcritical Flow
K Sum by GR= 0
Std Step Tol= 0.01
Critical Tol= 0.01
Num of Std Step Trials= 20
Max Error Tol= 0.3
Flow Tol Ratio= 0.001
Split Flow NTrial= 30
Split Flow Tol= 0.02
Split Flow Ratio= 0.02
Log Output Level= 0
Friction Slope Method= 1
Unsteady Friction Slope Method= 2
Unsteady Bridges Friction Slope Method= 1
Parabolic Critical Depth
Global Vel Dist= 0 , 0 , 0
Global Log Level= 0
CheckData=True
Encroach Param=-1 ,0,0, 0
Computation Interval=0.1SEC
Output Interval=1MIN
Instantaneous Interval=Max Profile
Mapping Interval=1HOUR
Computation Time Step Use Courant=        0
Computation Time Step Use Time Series=    0
Computation Time Step Count To Double=0
Computation Time Step Max Doubling=0
Computation Time Step Max Halving=0
Computation Time Step Residence Courant=0
Run HTab= 0
Run UNet= 0
Run Sediment= 0
Run PostProcess= 0
Run WQNet= 0
Run RASMapper= 0
UNET Theta= 0
UNET Theta Warmup= 0
UNET ZTol= 0
UNET ZSATol= 0
UNET MxIter= 0
UNET Max Iter WO Improvement= 0
UNET MaxInSteps= 0
UNET DtIC= 0
UNET DtMin= 0
UNET MaxCRTS= 0
UNET WFStab= 0
UNET SFStab= 0
UNET WFX= 1
UNET SFX= 1
UNET 1D Methodology=Finite Difference
UNET DSS MLevel= 1
UNET Pardiso=0
UNET DZMax Abort= 0
UNET Use Existing IB Tables= 0
UNET Froude Reduction=False
UNET Froude Limit= 0
UNET Froude Power= 0
UNET D1 Cores= 0
UNET D2 Coriolis=0
UNET D2 Cores= 0
UNET D2 Theta= 1
UNET D2 Theta Warmup= 1
UNET D2 Z Tol= 0.01
UNET D2 Volume Tol= 0.01
UNET D2 Max Iterations= 20
UNET D2 Equation= 0
UNET D2 RampUpFraction=0.1
UNET D2 TimeSlices= 1
UNET D2 BCVolumeCheck=0
UNET D1D2 MaxIter= 0
UNET D1D2 ZTol=0.01
UNET D1D2 QTol=0.1
UNET D1D2 MinQTol=1
DSS File=dss
Write IC File= 0
Write IC File at Fixed DateTime=0
Write IC File at Sim End=0
Echo Input=False
Echo Parameters=False
Echo Output=False
Write Detailed= 0
HDF Write Warmup=0
HDF Write Time Slices=0
HDF Flush=0
HDF Face Node Velocities=0
HDF Compression= 1
HDF Chunk Size= 1
HDF Spatial Parts= 1
HDF Use Max Rows=0
HDF Fixed Rows= 1
Calibration Method= 0
Calibration Iterations= 20
Calibration Max Change=0.05
Calibration Tolerance=0.2
Calibration Maximum=1.5
Calibration Minimum=0.5
Calibration Optimization Method= 1
WQ AD Non Conservative
WQ ULTIMATE=-1
WQ Max Comp Step=1HOUR
WQ Output Interval=15MIN
WQ Output Selected Increments= 0
WQ Output face flow=0
WQ Output face velocity=0
WQ Output face area=0
WQ Output face dispersion=0
WQ Output cell volume=0
WQ Output cell surface area=0
WQ Output cell continuity=0
WQ Output cumulative cell continuity=0
WQ Output face conc=0
WQ Output face dconc_dx=0
WQ Output face courant=0
WQ Output face peclet=0
WQ Output face adv mass=0
WQ Output face disp mass=0
WQ Output cell mass=0
WQ Output cell source sink temp=0
WQ Output nsm pathways=0
WQ Output nsm derived pathways=0
WQ Output MaxMinRange=-1
WQ Daily Max Min Mean=-1
WQ Daily Range=0
WQ Daily Time=0
WQ Create Restart=0
WQ Fixed Restart=0
WQ System Summary=0
WQ Write To DSS=0
WQ Use Fixed Temperature=0
Sorting and Armoring Iterations= 10
XS Update Threshold= 0.02
Bed Roughness Predictor= 0
Hydraulics Update Threshold= 0.02
Energy Slope Method= 1
Volume Change Method= 1
Sediment Retention Method= 0
XS Weighting Method= 0
Number of US Weighted Cross Sections= 1
Number of DS Weighted Cross Sections= 1
Upstream XS Weight=0
Main XS Weight=1
Downstream XS Weight=0
Number of DS XS's Weighted with US Boundary= 1
Upstream Boundary Weight= 1
Weight of XSs Associated with US Boundary= 0
Number of US XS's Weighted with DS Boundary= 1
Downstream Boundary Weight= 0.5
Weight of XSs Associated with DS Boundary= 0.5
Percentile Method= 0
Sediment Output Level= 3
Mass or Volume Output= 0
Output Increment Type= 1
Profile and TS Output Increment= 1
XS Output Flag= 0
XS Output Increment= 10
Write Gradation File= 0
Read Gradation Hotstart= 0
Write HDF5 File= 1
Write Binary Output= 1
Write DSS Sediment File= 0
SV Curve= 0
Specific Gage Flag= 0

--- HAWESRN_T1.f01 (steady flow) ---

Flow Title=Flows
Program Version=5.07
Number of Profiles= 6
Profile Names=P100yr,P10yr,P25yr,P50yr,P500yr,P101yr
River Rch & RM=HAWESRN_T1,Main            ,5678
     535     250     354     441     783     651
River Rch & RM=HAWESRN_T1,Main            ,5184
     597     279     395     493     876     727
Boundary for River Rch & Prof#=HAWESRN_T1,Main            , 1
Up Type= 0
Dn Type= 3
Dn Slope=0.04096
Boundary for River Rch & Prof#=HAWESRN_T1,Main            , 2
Up Type= 0
Dn Type= 3
Dn Slope=0.04096
Boundary for River Rch & Prof#=HAWESRN_T1,Main            , 3
Up Type= 0
Dn Type= 3
Dn Slope=0.04096
Boundary for River Rch & Prof#=HAWESRN_T1,Main            , 4
Up Type= 0
Dn Type= 3
Dn Slope=0.04096
Boundary for River Rch & Prof#=HAWESRN_T1,Main            , 5
Up Type= 0
Dn Type= 3
Dn Slope=0.04096
Boundary for River Rch & Prof#=HAWESRN_T1,Main            , 6
Up Type= 0
Dn Type= 3
Dn Slope=0.04096
DSS Import GetInterval= 0
DSS Import GetPeak= 0
DSS Import FillOption= 0

--- HAWESRN_T1.g01 (geometry) ---

Geom Title=Geometry
Program Version=5.07

River Reach=HAWESRN_T1      ,Main
Reach XY= 30
     2484741.755      589459.214     2484574.933      589473.127
      2484448.51      589568.922     2484114.836      589641.759
     2483324.105      589674.222     2483187.975      589622.802
     2483079.663      589712.365     2482877.637      589748.096
     2482782.421      589808.142      2482634.84      589825.974
     2482538.223      589943.998     2482483.192      589930.293
     2482391.661      589843.453     2482298.417      589829.237
     2482101.453      589906.193     2481955.375      589876.819
      2481650.15      589985.1642481385.51956201589962.580590356
2481355.60413558589874.2936001672481362.90058105589726.175757122
2481330.06657643589645.1852124042481192.89340159589627.673743275
2480939.58784664589750.018829632 2480726.1264354589907.902228406
2480682.77284415590035.452420932     2480496.792      590010.282
     2480308.376      590079.796     2480136.199      590099.682
     2479962.359      590041.593     2479850.226       590056.53

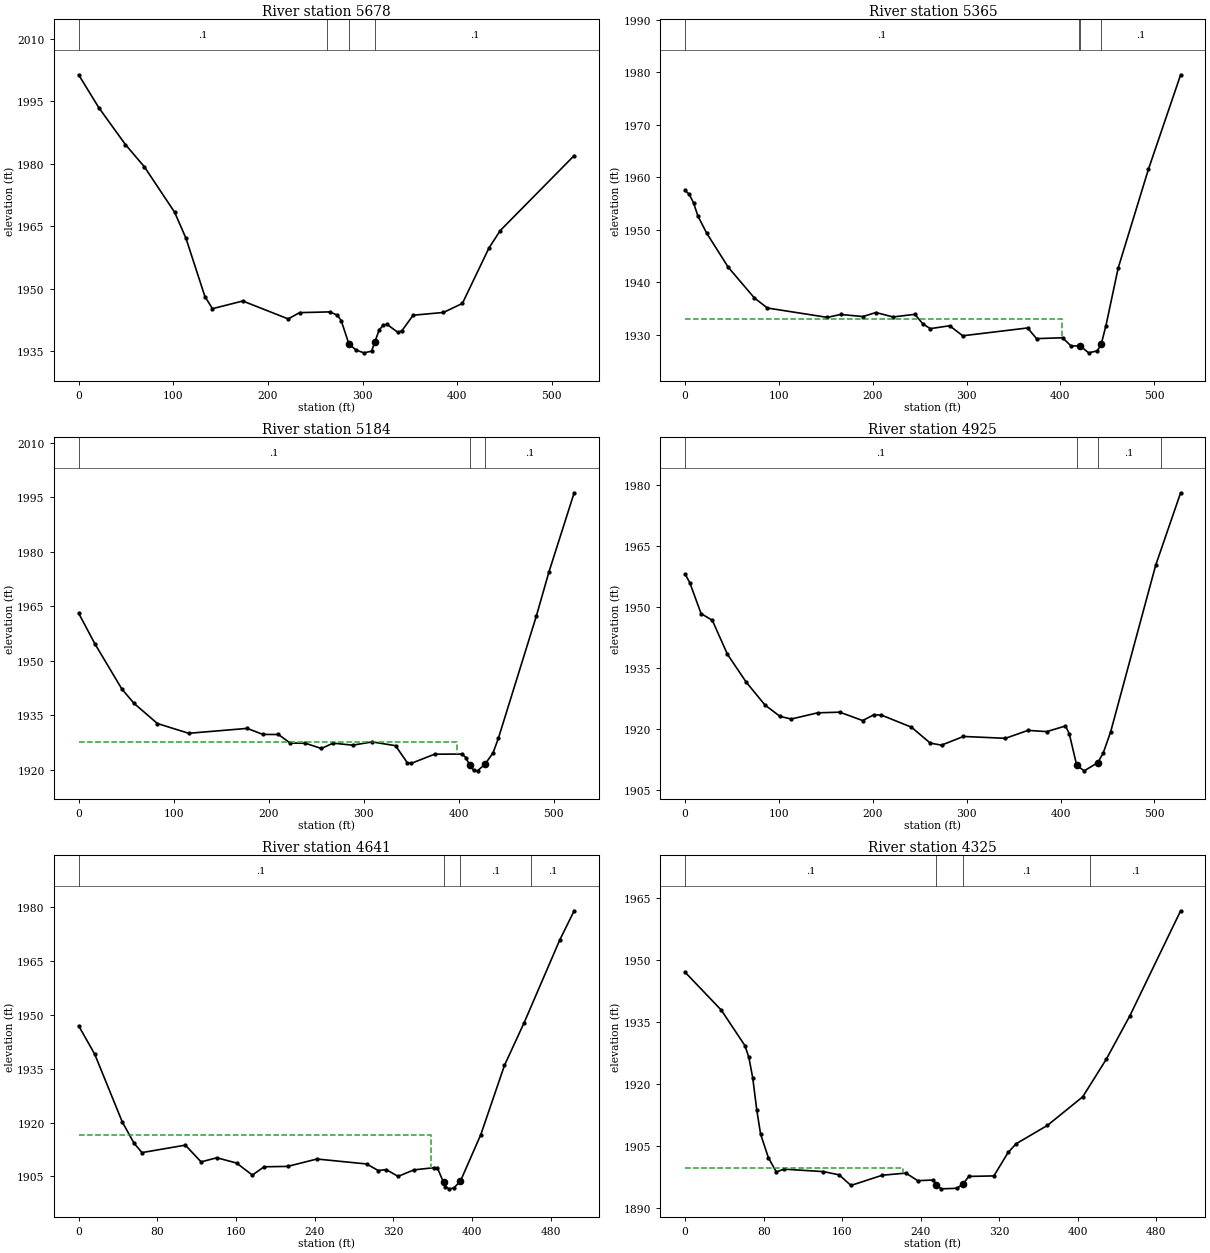
Type RM Length L Ch R = 1 ,5678    ,319.3,312.1,306.2
XS GIS Cut Line= 2
2484732.62235054589153.5303599292484735.56593899589677.054249639
#Sta/Elev= 30
       0 2001.33    21.4 1993.41    49.4 1984.59    69.4 1979.26   101.4 1968.34
   113.4 1962.08   133.4 1948.11   141.4 1945.19   173.4 1947.03   221.4 1942.73
   233.4 1944.24   265.4 1944.42   273.4 1943.62   277.4 1942.31   285.4  1936.8
   292.9 1935.27   301.4 1934.59   309.4 1934.99     313 1937.22   317.4 1940.06
   321.7 1941.21   325.7 1941.44   337.4 1939.48   341.6 1939.92   353.4 1943.62
   385.4 1944.28   405.4 1946.45   433.4 1959.72   445.4 1963.94   523.5 1981.93
#Mann= 4 ,-1 , 0
       0      .1       0  262.61      .1       0   285.4    .045       0
     313      .1       0
Bank Sta=285.4,313
XS Rating Curve= 0 ,0
Exp/Cntr=0.3,0.1

Type RM Length L Ch R = 1 ,5365    ,177.9,180.9,185
XS GIS Cut Line= 2
2484243.37647543589191.1039147412484508.96139806589647.695499015
#Sta/Elev= 30
       0 1957.45     4.4 1956.71       9 1955.09    13.6  1952.6    22.9 1949.35
      46 1942.81    73.8 1936.98    87.7 1935.05   151.5 1933.27   165.8 1933.82
   189.5 1933.43   203.4 1934.19   221.7 1933.35     245 1933.85   253.3 1932.05
   261.3 1931.12     282 1931.67   295.9 1929.76   365.1 1931.25   374.6 1929.22
   402.3 1929.38   411.6 1927.79   420.9 1927.88   430.1 1926.51   439.4 1926.88
   443.6  1928.2   448.6 1931.71   461.6 1942.65   493.8 1961.45   528.2 1979.49
#Mann= 4 ,-1 , 0
       0      .1       0  420.24      .1       0   420.9    .045       0
   443.6      .1       0
#XS Ineff= 2 , 0
          402.16 1933.05
Permanent Ineff=
       F       F
Bank Sta=420.9,443.6
XS Rating Curve= 0 ,0
Exp/Cntr=0.3,0.1

Type RM Length L Ch R = 1 ,5184    ,257,259.4,262.5
XS GIS Cut Line= 2
2484188.77725877589186.1349796652484307.65293341589693.908282692
#Sta/Elev= 30
       0 1963.06    17.2  1954.6    45.5  1942.2    58.3 1938.26    82.9 1932.71
   115.8 1930.02   177.4 1931.37   193.9 1929.71   210.3 1929.69   222.6 1927.33
   238.6 1927.28   255.5 1925.84   267.8 1927.31   288.3 1926.75   308.9 1927.65
   333.5 1926.61   345.9 1921.92     350 1921.74   374.6 1924.27   403.4 1924.31
   407.5 1923.35   411.7 1921.17   415.7 1919.84   419.8 1919.69     428 1921.63
   436.2 1924.68   441.7 1928.62   481.6  1962.2   494.9 1974.37   521.5  1996.2
#Mann= 3 ,-1 , 0
       0      .1       0   411.7    .045       0     428      .1       0
#XS Ineff= 2 , 0
          398.34 1927.58
Permanent Ineff=
       F       F
Bank Sta=411.7,428
XS Rating Curve= 0 ,0
Exp/Cntr=0.3,0.1

Type RM Length L Ch R = 1 ,4925    ,284.2,283.7,281.3
XS GIS Cut Line= 2
2484049.54590988589205.8685407032484029.09359447589733.501183243
#Sta/Elev= 30
       0 1958.06       5 1955.93      17 1948.35      29 1946.69    45.1 1938.35
    65.1  1931.5    85.1 1925.88   101.1 1923.09   113.1 1922.43   141.1 1923.95
   164.7 1924.12   189.2 1922.06   201.2 1923.48   209.2  1923.4   241.2 1920.42
   261.2 1916.52   273.2 1916.01   296.6 1918.15   341.3 1917.69   365.3 1919.64
   385.3 1919.34   405.3 1920.72   409.3 1918.86   417.3 1911.02   425.3  1909.7
   439.6  1911.7   445.4 1914.01   453.4 1919.26   501.4 1960.22     528 1978.03
#Mann= 4 ,-1 , 0
       0      .1       0   417.3    .045       0   439.6      .1       0
  506.83      .1       0
Bank Sta=417.3,439.6
XS Rating Curve= 0 ,0
Exp/Cntr=0.3,0.1

Type RM Length L Ch R = 1 ,4641    ,315.8,316.1,315.1
XS GIS Cut Line= 2
2483736.44786482589294.5207834182483761.20249564589797.729282071
#Sta/Elev= 30
       0    1947    16.4 1939.05    44.4 1920.15    56.4 1914.22    64.4 1911.62
   108.5  1913.7   124.5 1909.03   140.5 1910.18   160.6  1908.7   176.6 1905.35
   188.6 1907.66   212.5 1907.77   242.3 1909.83   292.7 1908.45   304.7 1906.61
   312.7 1906.88   324.8 1904.98   340.8  1906.8   361.3 1907.41   364.8 1907.29
     3711903.297   372.8 1902.09   376.8 1901.51   381.3 1901.73   388.1 1903.62
   408.9 1916.65   432.9 1935.93     453  1947.9     489 1970.85   503.8 1979.08
#Mann= 4 ,-1 , 0
       0      .1       0     371    .045       0   388.1      .1       0
  460.41      .1       0
#XS Ineff= 2 , 0
          358.11 1916.46
Permanent Ineff=
       F       F
Bank Sta=371,388.1
XS Rating Curve= 0 ,0
Exp/Cntr=0.3,0.1

Type RM Length L Ch R = 1 ,4325    ,291.3,288.7,283.8
XS GIS Cut Line= 2
2483437.01685611589390.0403139062483450.12027035589894.572812559
#Sta/Elev= 30
       0 1947.04    36.9 1937.85    60.9 1929.27    64.9 1926.46    68.9 1921.42
      73 1913.65    76.9 1907.81    84.9 1902.07    92.9 1898.67   100.9 1899.34
   140.9 1898.74   156.9 1897.96   168.9 1895.39   200.9 1897.87   224.9 1898.38
   236.9 1896.55   252.9 1896.71     256 1895.57   260.9 1894.57   276.9  1894.7
   283.3  1895.8   288.9 1897.58   314.5  1897.7     329 1903.38     337 1905.47
     369 1909.93     405 1916.87     429 1925.98     453 1936.49   504.7 1961.92
#Mann= 4 ,-1 , 0
       0      .1       0     256    .045       0   283.3      .1       0
  412.81      .1       0
#XS Ineff= 2 , 0
          222.06 1899.54
Permanent Ineff=
       F       F
Bank Sta=256,283.3
XS Rating Curve= 0 ,0
Exp/Cntr=0.3,0.1

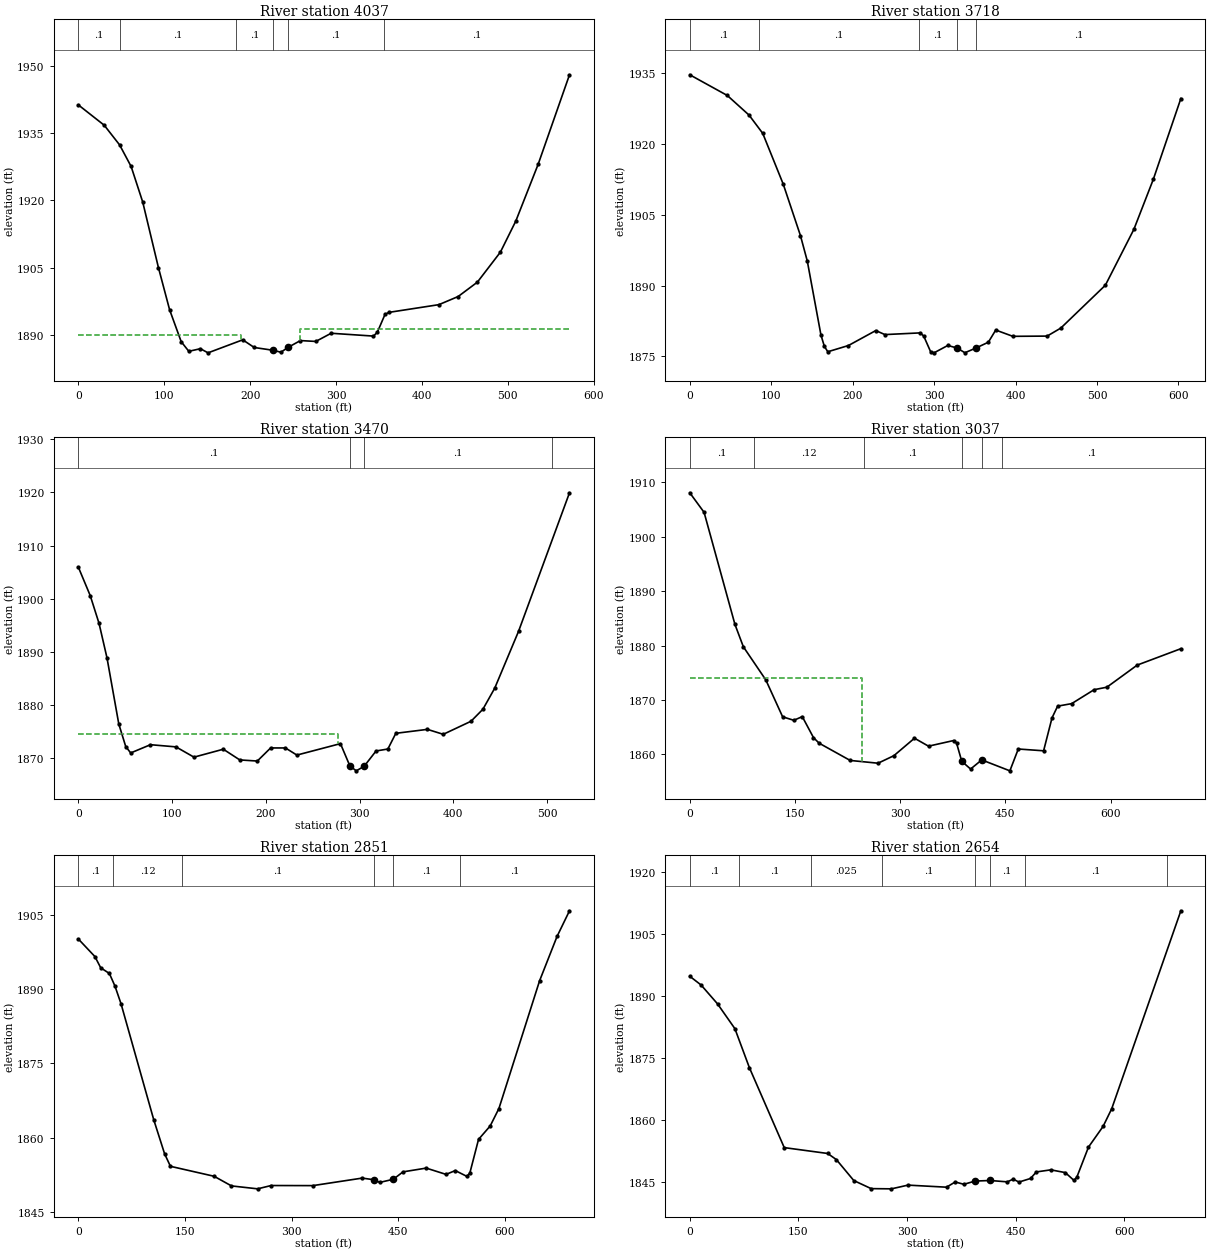
Type RM Length L Ch R = 1 ,4037    ,317.1,318.7,319.7
XS GIS Cut Line= 2
2483068.76649414589420.0463502542483326.42561189589930.740866329
#Sta/Elev= 30
       0 1941.27    30.1 1936.75      48 1932.37    61.4 1927.57    74.9 1919.66
    93.2 1905.06   106.2 1895.68   119.7 1888.56   128.6 1886.41   142.1 1886.99
     151 1886.07   191.4 1888.97   204.8 1887.26   226.4 1886.65   235.9 1886.21
   244.2 1887.29   258.6  1888.8   276.5 1888.61   294.4 1890.43   343.7  1889.8
   348.2 1890.67   357.1 1894.62   361.6 1895.08   419.9  1896.8   442.3 1898.61
   464.7 1901.81   491.5 1908.49   509.5 1915.43   535.5 1928.06     572 1947.99
#Mann= 6 ,-1 , 0
       0      .1       0   48.52      .1       0  183.71      .1       0
   226.4    .045       0   244.2      .1       0  356.08      .1       0
#XS Ineff= 2 , 0
          189.94 1890.11  258.11          1891.4
Permanent Ineff=
       F       F
Bank Sta=226.4,244.2
XS Rating Curve= 0 ,0
Exp/Cntr=0.3,0.1

Type RM Length L Ch R = 1 ,3718    ,247.7,247.9,247
XS GIS Cut Line= 2
2482789.87575729589425.7082063672482976.62662211 589999.06582127
#Sta/Elev= 30
       0 1934.69    46.1  1930.3    72.8 1926.14    89.6 1922.27   114.8 1911.49
   135.9  1900.6   144.3 1895.21   161.1  1879.5   165.3 1877.11   169.5 1875.98
   194.8  1877.3   228.4 1880.47   239.6 1879.62   283.1 1879.98   287.3 1879.29
   295.7    1876   299.9 1875.75   316.8 1877.31   328.2 1876.78   337.8 1875.77
   351.5 1876.78   366.6    1878   375.7 1880.58   396.7 1879.25   438.8  1879.3
   455.6    1881   510.3 1890.08   545.3 1901.92   569.2 1912.54     603 1929.66
#Mann= 5 ,-1 , 0
       0      .1       0   84.45      .1       0  282.06      .1       0
   328.2    .045       0   351.5      .1       0
Bank Sta=328.2,351.5
XS Rating Curve= 0 ,0
Exp/Cntr=0.3,0.1

Type RM Length L Ch R = 1 ,3470    ,419.8,433.4,431.8
XS GIS Cut Line= 2
2482571.63760493589534.0281413922482739.32316879590030.462607182
#Sta/Elev= 30
       0 1905.91    12.6  1900.6      22 1895.39    30.5  1888.9    43.1 1876.47
    50.5 1872.24    55.8 1871.04    76.9 1872.59   104.1 1872.18   123.3 1870.25
   154.6 1871.74   172.2 1869.73   190.9 1869.52   205.1 1871.98   220.9 1871.98
   233.1 1870.64   279.6 1872.79   289.7 1868.59   296.5 1867.68   304.9 1868.54
   317.6 1871.41   330.2 1871.78   338.7 1874.73   372.4 1875.47   389.3 1874.54
   418.9 1876.99   431.6 1879.25   444.2  1883.2   469.6 1893.87     524 1919.91
#Mann= 4 ,-1 , 0
       0      .1       0   289.7    .045       0   304.9      .1       0
  504.88     .12       0
#XS Ineff= 2 , 0
          277.11 1874.62
Permanent Ineff=
       F       F
Bank Sta=289.7,304.9
XS Rating Curve= 0 ,0
Exp/Cntr=0.3,0.1

Type RM Length L Ch R = 1 ,3037    ,188.1,186,181.8
XS GIS Cut Line= 3
2482334.75441228 589430.524877992482345.89238355590025.119808419
2482425.84430353590093.922270972
#Sta/Elev= 30
       0 1908.05    20.4 1904.46    64.4 1883.88    76.4 1879.77   108.4 1873.69
   132.4 1866.91   148.4 1866.27   160.4 1866.95   176.4 1863.09   184.4 1862.07
   228.7  1858.9   268.4 1858.39     291 1859.77   320.4 1862.98   340.4 1861.52
   376.4 1862.56   380.4 1862.08   387.81858.743   400.4 1857.32   416.31859.001
   456.4 1856.99   468.4    1861   504.5 1860.67   516.5 1866.72   524.5 1868.87
   544.5 1869.33   576.5 1871.89   594.7 1872.35     638 1876.41   700.2 1879.42
#Mann= 6 ,-1 , 0
       0      .1       0   90.99     .12       0  248.22      .1       0
   387.8    .045       0   416.3      .1       0  445.08      .1       0
#XS Ineff= 2 , 0
          244.96 1873.98
Permanent Ineff=
       F       F
Bank Sta=387.8,416.3
XS Rating Curve= 0 ,0
Exp/Cntr=0.3,0.1

Type RM Length L Ch R = 1 ,2851    ,193,196.1,199.8
XS GIS Cut Line= 2
     2482083.682      589472.2192482227.71546367590148.001491566
#Sta/Elev= 30
       0  1900.1    23.2 1896.57    31.4  1894.3    43.6 1893.15    51.5 1890.58
      60 1887.02     106  1863.6   121.3 1856.71   129.5 1854.19   190.9 1852.18
   215.4 1850.23   252.2 1849.64   271.2 1850.31   329.9 1850.29   399.3 1851.81
   415.3 1851.49     424 1850.94   443.1 1851.57   456.7 1853.07   489.4 1853.83
   517.3 1852.56   530.3 1853.33   546.7 1852.15   550.8 1852.84     563 1859.63
   579.4 1862.34   591.7 1865.87   648.9 1891.67   673.5 1900.64     691 1905.82
#Mann= 6 ,-1 , 0
       0      .1       0    48.3     .12       0  145.98      .1       0
   415.3    .045       0   443.1      .1       0  536.71      .1       0
Bank Sta=415.3,443.1
XS Rating Curve= 0 ,0
Exp/Cntr=0.3,0.1

Type RM Length L Ch R = 1 ,2654    ,174.4,170.8,168.8
XS GIS Cut Line= 2
2481979.78160972589468.560814286 2481992.7670698590146.357085628
#Sta/Elev= 30
       0 1894.71    15.7 1892.58    38.3 1888.03    62.3 1882.02    82.3 1872.58
   130.4 1853.23   190.4 1851.81   202.4 1850.32   226.4 1845.26   250.4  1843.3
   278.4 1843.25   301.2 1844.15   354.4 1843.65   366.4 1844.91   378.4 1844.35
   393.8 1845.13   414.4 1845.27   438.4 1844.94   446.4  1845.6   454.4 1844.89
   470.4 1845.76   478.4 1847.34   498.4 1847.85   518.4 1847.18   530.4 1845.28
   534.4 1846.12   550.4 1853.36   570.5 1858.35   582.4 1862.62   677.9 1910.56
#Mann= 8 ,-1 , 0
       0      .1       0    68.4      .1       0  166.82    .025       0
  265.25      .1       0   393.8    .045       0   414.4      .1       0
   462.1      .1       0  658.95     .12       0
Bank Sta=393.8,414.4
XS Rating Curve= 0 ,0
Exp/Cntr=0.3,0.1

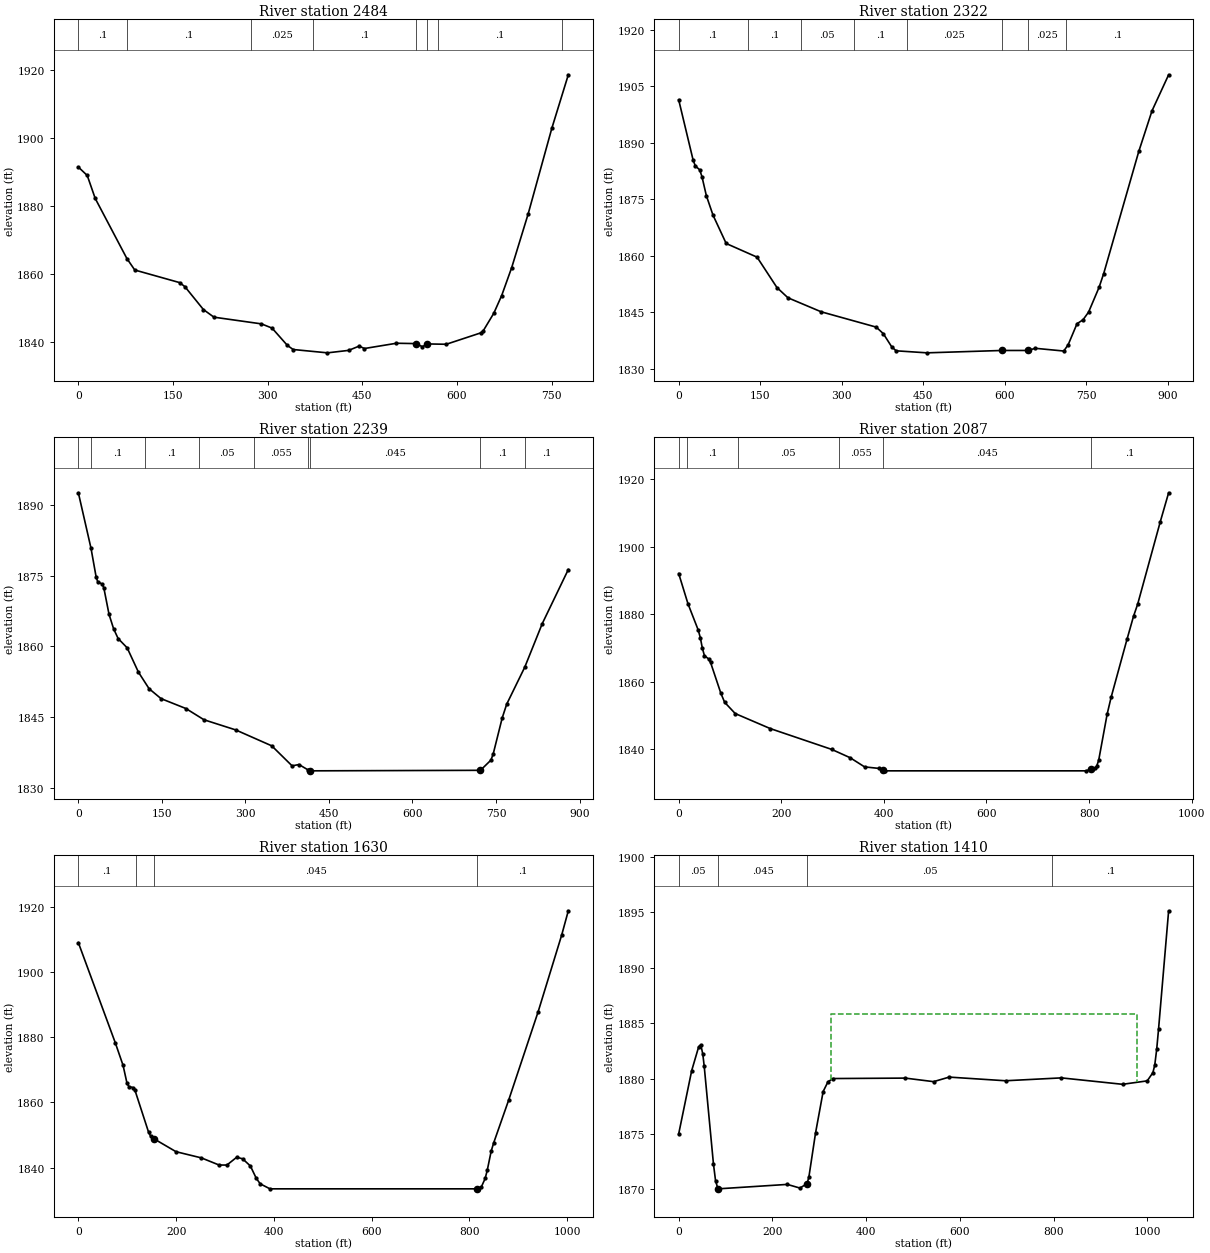
Type RM Length L Ch R = 1 ,2484    ,159.3,161.8,165.5
XS GIS Cut Line= 2
2481670.40495608589409.394022331 2481897.9277145590151.842912522
#Sta/Elev= 30
       0 1891.46    14.1 1888.99    26.7 1882.25    76.9 1864.59    89.4 1861.21
   160.5 1857.51   168.9 1856.31   198.2 1849.59   214.9 1847.35   290.2 1845.38
     307 1844.14   331.3 1839.05   340.4 1837.85   394.8 1836.87   428.3 1837.59
     445 1838.85   453.4 1838.14   504.2 1839.69   535.21839.584   545.4 1838.66
   552.3 1839.49   583.1 1839.39   637.5 1842.72   641.7 1843.35   658.4  1848.5
   670.9  1853.7   686.8 1861.93   712.8 1877.65   750.4 1902.87   776.5 1918.58
#Mann= 8 ,-1 , 0
       0      .1       0   76.97      .1       0  274.05    .025       0
  372.59      .1       0   535.2    .045       0   552.3      .1       0
  569.67      .1       0  766.76     .12       0
Bank Sta=535.2,552.3
XS Rating Curve= 0 ,0
Exp/Cntr=0.3,0.1

Type RM Length L Ch R = 1 ,2322    ,193.7,82.9,118.1
XS GIS Cut Line= 2
2481574.33576208589372.7453411462481726.51662177590260.978646171
#Sta/Elev= 30
       0  1901.4    26.5 1885.41    30.6 1883.82    38.7 1882.78    42.8 1880.99
    50.9 1875.93    63.1 1870.77    87.4 1863.22   144.2 1859.59   180.7 1851.53
     201  1848.8   262.1 1845.08   363.4 1841.01   376.4 1839.27   391.8 1835.79
   399.9 1834.72   456.7 1834.18   594.6 1834.81   643.2 1834.81   655.6 1835.39
   708.3 1834.66   716.4 1836.32   732.7 1841.92   743.7 1842.95     754 1845.01
   773.3 1851.59   781.8 1855.25   846.3 1887.68   870.6 1898.45   901.2 1908.03
#Mann= 8 ,-1 , 0
       0      .1       0  127.15      .1       0   224.7     .05       0
  322.24      .1       0  419.78    .025       0   594.6    .045       0
   643.2    .025       0  712.41      .1       0
Bank Sta=594.6,643.2
XS Rating Curve= 0 ,0
Exp/Cntr=0.3,0.1

Type RM Length L Ch R = 1 ,2239    ,127.6,152.2,197
XS GIS Cut Line= 2
 2481496.2785633589392.5228213632481643.71385483 590259.88150452
#Sta/Elev= 30
       0 1892.63    22.7 1880.86    31.9 1874.76    34.9 1873.68      43 1873.24
    45.8  1872.4    55.1  1866.8    63.3 1863.74    71.4 1861.67    87.6  1859.7
   107.9 1854.52     127 1851.01   148.5  1848.9   193.1  1846.8   225.6 1844.41
   282.4 1842.26   347.3 1838.87   383.8 1834.62   396.1  1834.9   412.2 1833.78
   415.4 1833.61   416.3 1833.56     722 1833.67   740.8 1835.83   744.9 1837.13
   761.1  1844.8   769.2 1847.73   801.6 1855.58     833 1864.83   879.8 1876.33
#Mann= 9 ,-1 , 0
       0      .1       0   22.04      .1       0  119.58      .1       0
  217.12     .05       0  314.66    .055       0   412.2    .025       0
   415.4    .045       0     722      .1       0  802.37      .1       0
Bank Sta=415.4,722
XS Rating Curve= 0 ,0
Exp/Cntr(USF)=0,0
Exp/Cntr=0.3,0.1

Type RM Length L Ch R = 1 ,2087    ,297.8,456.4,159.7
XS GIS Cut Line= 2
2481424.12093899589408.7604875582481458.41010981590363.254975598
#Sta/Elev= 30
       0 1892.01    18.1 1883.06    38.2 1875.22    42.2 1872.99    46.2 1869.86
    50.2  1867.7    58.2 1866.72    62.2 1865.65    82.2 1856.55    89.6 1853.86
   110.2 1850.53   178.5 1846.08   298.3 1839.91   334.3 1837.44   362.4 1834.73
   390.4 1834.28   398.7 1833.71   402.4 1833.56   794.6 1833.56   804.4 1834.16
   810.7 1834.29   814.7 1834.89   818.7 1836.65   835.3  1850.4     843 1855.35
   873.9 1872.49   886.7 1879.36   894.7 1882.91   938.7 1907.28   955.1 1915.92
#Mann= 6 ,-1 , 0
       0      .1       0   17.19      .1       0   115.4     .05       0
  311.83    .055       0   398.7    .045       0   804.4      .1       0
Bank Sta=398.7,804.4
XS Rating Curve= 0 ,0
Exp/Cntr=0.3,0.1

Type RM Length L Ch R = 1 ,1630    ,147,220.5,516.8
XS GIS Cut Line= 2
 2481262.4239695589431.372554664 2481311.3859939590432.481213517
#Sta/Elev= 30
       0 1908.93    75.6 1878.26    91.5 1871.35    99.6 1865.83   103.6 1864.85
   111.7 1864.57   115.7 1863.79   143.7 1850.88   147.7 1849.75   155.7 1848.79
   199.8 1844.93   251.8 1843.03   287.9 1840.85   303.9 1840.84   323.9 1843.23
     336 1842.76   351.9 1840.56     364 1836.78     372  1835.1     392 1833.56
   816.5 1833.56   824.5 1834.18   832.2 1836.73   836.5 1839.25   844.5 1845.09
   849.7 1847.66   880.6 1860.86   940.6 1887.78   988.7 1911.23  1002.3 1918.69
#Mann= 4 ,-1 , 0
       0      .1       0  117.71     .05       0   155.7    .045       0
   816.5      .1       0
Bank Sta=155.7,816.5
XS Rating Curve= 0 ,0
Exp/Cntr=0.3,0.1

Type RM Length L Ch R = 1 ,1410    ,487.4,371.2,335.3
XS GIS Cut Line= 6
2480963.31831557589488.9137818632481105.65297253589764.868684843
2481014.01864611589868.1344785542481037.54058158590084.939717107
2481092.05765252 590322.999800222481112.26807678590456.148878122
#Sta/Elev= 30
       0    1875    27.8 1880.72    42.7 1882.87    47.2 1883.05    51.5  1882.2
    54.5 1881.11    74.2 1872.29    78.7 1870.77    83.81870.044    84.2 1870.04
   231.8 1870.44   258.8 1870.11   274.2 1870.52     278 1871.15     292 1875.07
   308.3 1878.83   318.5  1879.7   329.1    1880   483.5 1880.04   543.9 1879.72
   577.2 1880.13   697.4  1879.8   816.7 1880.06   947.2 1879.48   999.8 1879.79
  1011.9 1880.53  1015.9 1881.22    1020 1882.63    1024 1884.47  1045.5 1895.15
#Mann= 4 ,-1 , 0
       0     .05       0    83.8    .045       0   274.2     .05       0
   797.3      .1       0
#XS Ineff= 1 ,-1
  326.03     977 1885.85
Permanent Ineff=
       F
Bank Sta=83.8,274.2
XS Rating Curve= 0 ,0
Exp/Cntr=0.3,0.1

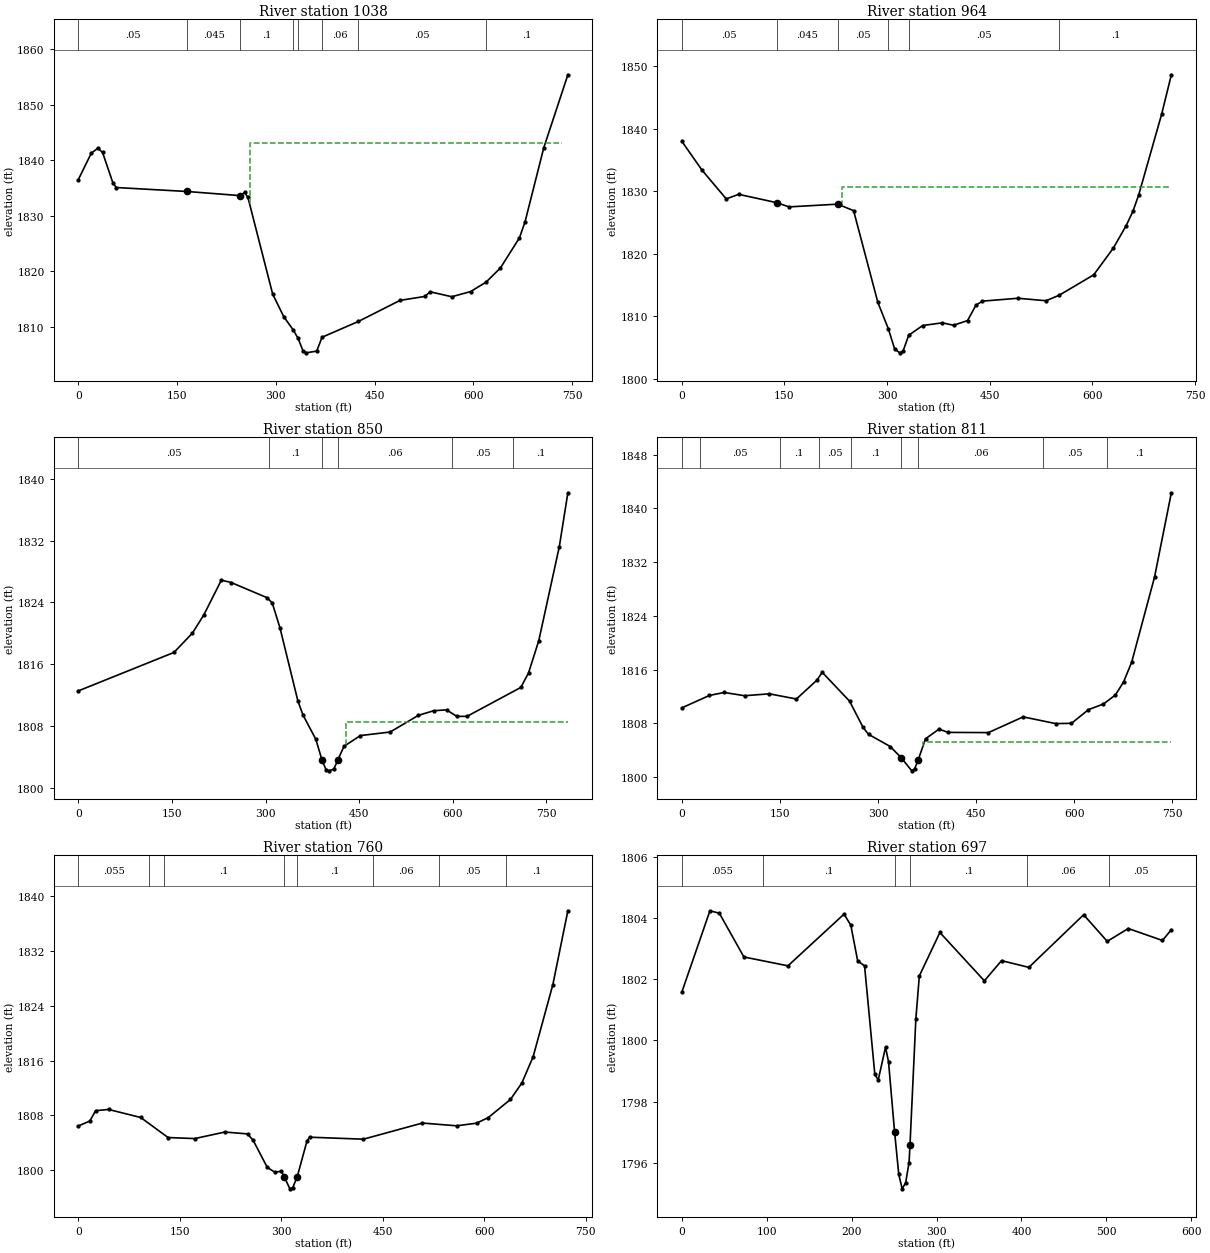
Type RM Length L Ch R = 1 ,1038    ,82.1,74.9,61.5
XS GIS Cut Line= 6
2480632.26138721589733.6464298252480793.21372125589935.283648818
2480821.91119961  590032.04879242480878.49713825590279.438773277
2480894.55940692590343.1175444192480908.10803022590406.667177975
#Sta/Elev= 30
       0  1836.5    19.7 1841.26    29.6 1842.14    36.8 1841.39    52.8  1835.8
    57.9 1835.07   164.9 1834.36   245.71833.614   252.4 1834.18   257.5 1833.31
   295.1  1815.9   311.8 1811.85   326.3 1809.44   333.7 1807.92     341 1805.73
   345.8 1805.31     362 1805.62   370.1 1808.12   425.3 1810.96   488.6 1814.76
   526.1 1815.46   534.3  1816.3   567.1 1815.41   595.7 1816.34   619.1 1818.03
     641 1820.59   669.9 1826.02   678.4 1828.91   706.8 1842.23   743.4 1855.37
#Mann= 8 ,-1 , 0
       0     .05       0   164.9    .045       0   245.7      .1       0
   326.3     .06       0   333.7    .045       0   370.1     .06       0
   425.3     .05       0   619.1      .1       0
#XS Ineff= 1 ,-1
  260.12   734.2 1843.14
Permanent Ineff=
       F
Bank Sta=164.9,245.7
XS Rating Curve= 0 ,0
Exp/Cntr(USF)=0,0
Exp/Cntr=0.3,0.1

Type RM Length L Ch R = 1 ,964     ,127.5,114,122.4
XS GIS Cut Line= 6
2480636.49888104589770.6693770872480625.83102642589834.676504798
2480670.63601581589914.6854144382480715.44100521589948.822549217
2480752.77849638 589956.290047452480853.05632979590409.673868741
#Sta/Elev= 30
       0 1837.97    29.5 1833.36    64.9 1828.76    83.1 1829.49   138.5 1828.16
   156.6 1827.48   227.7 1827.92     251 1826.88   286.4 1812.22   301.8 1807.97
     311 1804.75   318.6 1804.14   323.3 1804.42   331.5 1806.95     352 1808.51
   380.7 1808.94     397 1808.55   417.5  1809.3   429.8 1811.77   439.3 1812.41
   491.3 1812.87   532.2 1812.47   551.7 1813.37   601.9 1816.62   630.6 1820.91
   649.1 1824.45   659.2 1826.79   667.6  1829.4     701 1842.26   715.3 1848.61
#Mann= 6 ,-1 , 0
       0     .05       0   138.5    .045       0   227.7     .05       0
   301.8    .045       0   331.5     .05       0   551.7      .1       0
#XS Ineff= 2 , 0
                           233.8         1830.65
Permanent Ineff=
       F       F
Bank Sta=138.5,227.7
XS Rating Curve= 0 ,0
Exp/Cntr(USF)=0,0
Exp/Cntr=0.3,0.1

Type RM Length L Ch R = 1 ,850     ,39.6,38.1,38.6
XS GIS Cut Line= 3
2480461.91494581589707.0106545142480625.62746598589867.348451436
2480751.93932059590408.292698349
#Sta/Elev= 30
       0 1812.52   153.2  1817.5   182.8    1820   201.3 1822.39   229.2 1826.87
   245.1 1826.56   302.6 1824.59   310.8 1823.91   323.2 1820.68   351.9 1811.21
   360.1 1809.39   380.7 1806.24   390.6 1803.53   397.1  1802.3   401.2 1802.16
   409.4 1802.37     4161803.583   425.8 1805.34   452.1 1806.73   499.8 1807.19
     545 1809.35   569.6 1809.95   590.1 1810.06   606.6 1809.22     623 1809.22
   709.3 1812.97   721.6 1814.86     738 1819.03   770.9 1831.21   784.6 1838.19
#Mann= 6 ,-1 , 0
       0     .05       0  305.92      .1       0   390.6    .045       0
     416     .06       0  599.34     .05       0  697.15      .1       0
#XS Ineff= 2 , 0
                          428.48         1808.51
Permanent Ineff=
       F       F
Bank Sta=390.6,416
XS Rating Curve= 0 ,0
Exp/Cntr(USF)=0,0
Exp/Cntr=0.5,0.3

Type RM Length L Ch R = 1 ,811     ,48.5,51.2,51
XS GIS Cut Line= 3
2480446.13061412589747.9508516412480590.81728196589906.634089431
2480731.82887203590421.394675879
#Sta/Elev= 30
       0 1810.32    42.2 1812.17    64.8 1812.61    95.9 1812.13   133.9 1812.41
   175.2 1811.64   206.4 1814.43   214.7 1815.61   256.5 1811.32   277.2  1807.4
   285.5 1806.38   318.7 1804.57   335.6 1802.88   351.6 1800.95     356 1801.27
   361.4 1802.57   372.6 1805.72   393.3 1807.16     407 1806.67   468.8 1806.64
   521.9 1808.98   571.7 1807.98   595.8 1808.02   621.8 1810.06   644.6 1810.89
   662.9 1812.23   675.4 1814.17   687.8 1817.11   722.8 1829.79   748.5 1842.33
#Mann= 9 ,-1 , 0
       0    .055       0   27.81     .05       0  149.41      .1       0
  209.44     .05       0  258.09      .1       0   335.6    .045       0
   361.4     .06       0  552.57     .05       0  650.73      .1       0
#XS Ineff= 2 , 0
          314.72  1804.5   368.9          1805.3
Permanent Ineff=
       F       F
Bank Sta=335.6,361.4
XS Rating Curve= 0 ,0
Exp/Cntr=0.5,0.3

Type RM Length L Ch R = 1 ,760     ,61.9,63.7,65.2
XS GIS Cut Line= 3
2480402.48081492  589779.07971062480542.76385901589913.498864138
2480696.53481244590420.119237516
#Sta/Elev= 30
       0 1806.48      17 1807.19    25.5  1808.7    44.7 1808.88    92.2 1807.71
   132.7 1804.79   172.1 1804.64   216.6 1805.59   250.1 1805.32   258.4  1804.4
   279.3 1800.45   290.6 1799.73   300.2 1799.89   304.4 1799.07   304.4 1799.06
   312.8 1797.32     317 1797.49   323.7 1799.11   337.9 1804.24     342 1804.84
   421.5 1804.55   508.5  1806.9   559.4  1806.5   588.7 1806.88   605.9 1807.69
   638.8 1810.33   655.6 1812.72   672.3 1816.54   701.5 1827.05   723.7 1837.81
#Mann= 8 ,-1 , 0
       0    .055       0  105.11     .05       0  126.48      .1       0
   304.4    .045       0   323.7      .1       0  435.39     .06       0
  533.89     .05       0  632.39      .1       0
Bank Sta=304.4,323.7
XS Rating Curve= 0 ,0
Exp/Cntr(USF)=0,0
Exp/Cntr=0.5,0.3

Type RM Length L Ch R = 1 ,697     ,130.7,130.8,130.3
XS GIS Cut Line= 3
2480374.90638787589808.1685069442480507.06703053589935.466143201
2480556.75528178590325.281857961
#Sta/Elev= 30
       0 1801.58    33.1 1804.24    44.2 1804.16    73.1 1802.73     125 1802.44
     191 1804.13     199 1803.77   207.1  1802.6   215.2 1802.44   227.3 1798.89
   231.3 1798.71   239.9 1799.78   243.4 1799.31   250.6    1797   255.5 1795.62
   259.5 1795.15   263.6 1795.35   267.6 1796.01  268.711796.583   275.6  1800.7
   279.7 1802.11   303.9 1803.53   356.3 1801.95   376.5 1802.61   408.7 1802.39
   473.2 1804.11     501 1803.24   525.7 1803.66     566 1803.27   576.5 1803.62
#Mann= 6 ,-1 , 0
       0    .055       0   95.43      .1       0   250.6    .045       0
  268.71      .1       0  406.07     .06       0  503.64     .05       0
Bank Sta=250.6,268.71
XS Rating Curve= 0 ,0
Exp/Cntr(USF)=0,0
Exp/Cntr=0.3,0.1

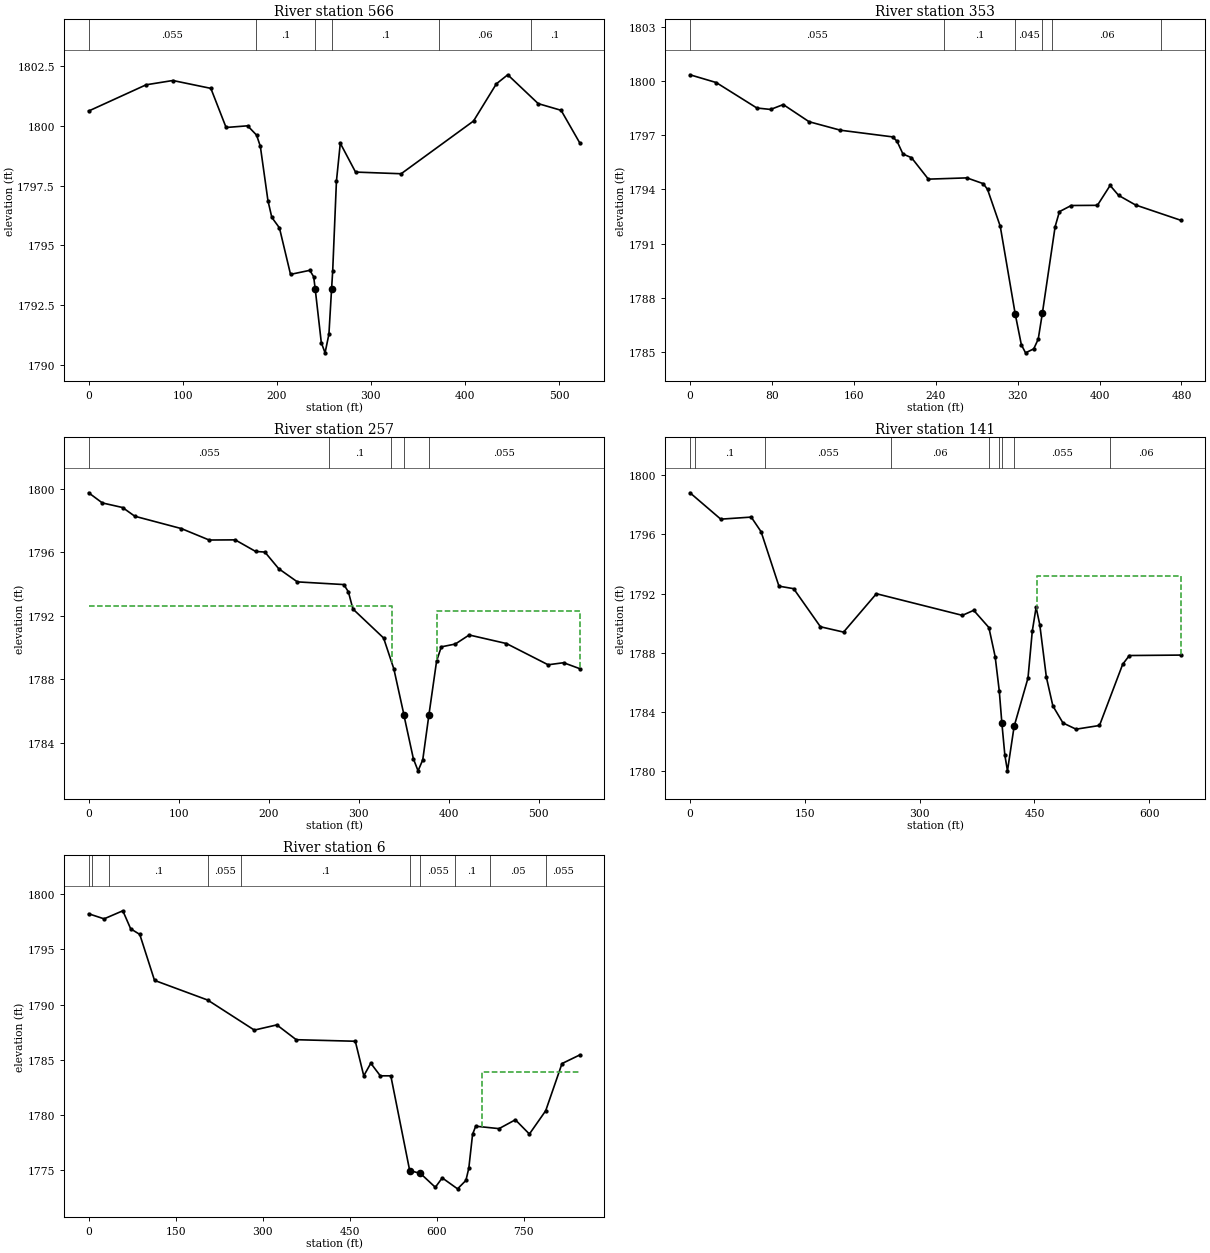
Type RM Length L Ch R = 1 ,566     ,207.2,213.2,217.7
XS GIS Cut Line= 2
2480358.73239505589806.4385078052480437.20489971590322.264438392
#Sta/Elev= 30
       0 1800.63    61.1 1801.73    89.5 1801.91   129.9 1801.58   146.1 1799.94
     169 1800.01   178.5 1799.62   182.5 1799.15   190.6 1796.87   194.7 1796.17
   202.8 1795.73   214.6 1793.78   235.1 1793.95   239.2 1793.68  240.841793.165
   247.3 1790.92   251.3 1790.49   255.4 1791.27   258.2 1793.15   259.4 1793.91
   263.4 1797.69   267.5 1799.28   283.7 1798.07   332.2    1798   409.1 1800.21
   433.4 1801.77   445.5 1802.15   477.9 1800.94   502.2 1800.66   521.8 1799.31
#Mann= 6 ,-1 , 0
       0    .055       0  177.69      .1       0  240.84    .045       0
   258.2      .1       0  372.75     .06       0  470.28      .1       0
Bank Sta=240.84,258.2
XS Rating Curve= 0 ,0
Exp/Cntr(USF)=0,0
Exp/Cntr=0.3,0.1

Type RM Length L Ch R = 1 ,353     ,89.6,96,100.6
XS GIS Cut Line= 3
 2480347.5663941589807.7161353662480218.66252413  589970.6700842
2480151.45553332590233.800802234
#Sta/Elev= 30
       0 1800.35    25.6 1799.92    65.3 1798.51    78.7 1798.43    91.1  1798.7
   116.3 1797.75   146.9 1797.28   197.9 1796.91   202.2 1796.67     208 1795.96
   216.3 1795.76   232.8 1794.57   270.4 1794.64   286.4 1794.32   290.6    1794
     303 1791.96   317.71787.076   323.6  1785.4   327.7 1784.95   335.7 1785.17
   340.1 1785.71   344.2 1787.17   356.6 1791.94   360.8 1792.77   372.3 1793.11
   397.9 1793.12   410.3 1794.22   418.6 1793.67   435.1 1793.14   479.4 1792.29
#Mann= 6 ,-1 , 0
       0    .055       0   247.9      .1       0   317.7    .045       0
   344.2      .1       0  353.97     .06       0  460.05     .05       0
Bank Sta=317.7,344.2
XS Rating Curve= 0 ,0
Exp/Cntr(USF)=0,0
Exp/Cntr=0.5,0.3

Type RM Length L Ch R = 1 ,257     ,117.2,115.1,114.3
XS GIS Cut Line= 2
2480324.00025256589811.1065270832479979.53962103590234.021811915
#Sta/Elev= 30
       0 1799.76    15.2 1799.12    37.7 1798.83    51.3 1798.28   103.1  1797.5
   133.9 1796.78   162.8 1796.79   185.5 1796.06   195.8 1796.02   211.2 1794.97
   231.9 1794.14   283.5 1793.97   288.6 1793.51   293.6 1792.43   327.7  1790.6
   339.1 1788.65   350.4 1785.73   350.4  1785.7   360.8 1782.98     366 1782.22
   371.2 1782.91  378.091785.761   386.6 1789.15   391.8 1790.04   407.4 1790.22
   422.8 1790.79   464.2 1790.25   510.5 1788.91   527.7 1789.04   545.4 1788.67
#Mann= 5 ,-1 , 0
       0    .055       0  266.56      .1       0  336.32    .055       0
   350.4    .045       0  378.09    .055       0
#XS Ineff= 2 , 0
          337.07  1792.6  387.03          1792.3
Permanent Ineff=
       F       F
Bank Sta=350.4,378.09
XS Rating Curve= 0 ,0
Exp/Cntr=0.5,0.3

Type RM Length L Ch R = 1 ,141     ,137.3,135.6,136.2
XS GIS Cut Line= 3
2480263.88169217589740.8467360892479962.17519886590080.572536775
2479890.36134083590253.050785473
#Sta/Elev= 30
       0  1798.8    40.2 1797.02      80 1797.16    92.9 1796.17   116.2  1792.5
   135.4 1792.33   170.4 1789.76   200.6  1789.4   243.5 1791.99   355.8 1790.53
   370.6 1790.87   390.4 1789.71   398.6 1787.75     404 1785.43   407.41783.249
   411.3 1781.09   414.7 1780.04   423.4 1783.04   441.5  1786.3   447.1 1789.46
   452.1 1791.07   456.9  1789.9   465.5 1786.36     474 1784.42   487.2 1783.27
   504.3 1782.85   534.9  1783.1   565.2 1787.23   573.9 1787.82   641.2 1787.85
#Mann= 9 ,-1 , 0
       0     .06       0    6.01      .1       0   97.33    .055       0
  262.27     .06       0  390.39      .1       0  403.56    .055       0
   407.4    .045       0   423.4    .055       0   548.7     .06       0
#XS Ineff= 2 , 0
                          452.76         1793.16
Permanent Ineff=
       F       F
Bank Sta=407.4,423.4
XS Rating Curve= 0 ,0
Exp/Cntr=0.5,0.3

Type RM Length L Ch R = 1 ,6       ,,,
XS GIS Cut Line= 4
2480284.00094061 589698.480869392479884.39401987590012.508192289
2479803.45007715 590135.036974272479822.48662775590324.929364313
#Sta/Elev= 30
       0 1798.23    26.6 1797.77    58.9  1798.5    72.4 1796.87    88.1 1796.36
   113.5  1792.2   205.1 1790.42   285.5  1787.7   324.3 1788.17   357.7 1786.83
   459.5 1786.69   474.1 1783.56   486.2  1784.7   502.6 1783.56   520.7 1783.56
   553.2 1774.99   571.8 1774.72   597.4 1773.47   609.3 1774.32   635.7 1773.33
   650.1 1774.09   655.1  1775.2   661.6 1778.27     667    1779   707.2 1778.78
   735.3 1779.58   759.5 1778.29   787.6  1780.4   815.7 1784.67   845.9 1785.44
#Mann= 10 ,-1 , 0
       0      .1       0    6.62     .06       0   35.77      .1       0
  205.69    .055       0  262.77      .1       0   553.2    .045       0
   571.8    .055       0  630.96      .1       0  690.85     .05       0
  788.52    .055       0
#XS Ineff= 2 , 0
                          678.35         1783.87
Permanent Ineff=
       F       F
Bank Sta=553.2,571.8
XS Rating Curve= 0 ,0
Exp/Cntr(USF)=0,0
Exp/Cntr=0.3,0.1
LCMann Table=0

Chan Stop Cuts=-1
Use User Specified Reach Order=0
Composite Channel Slope=5